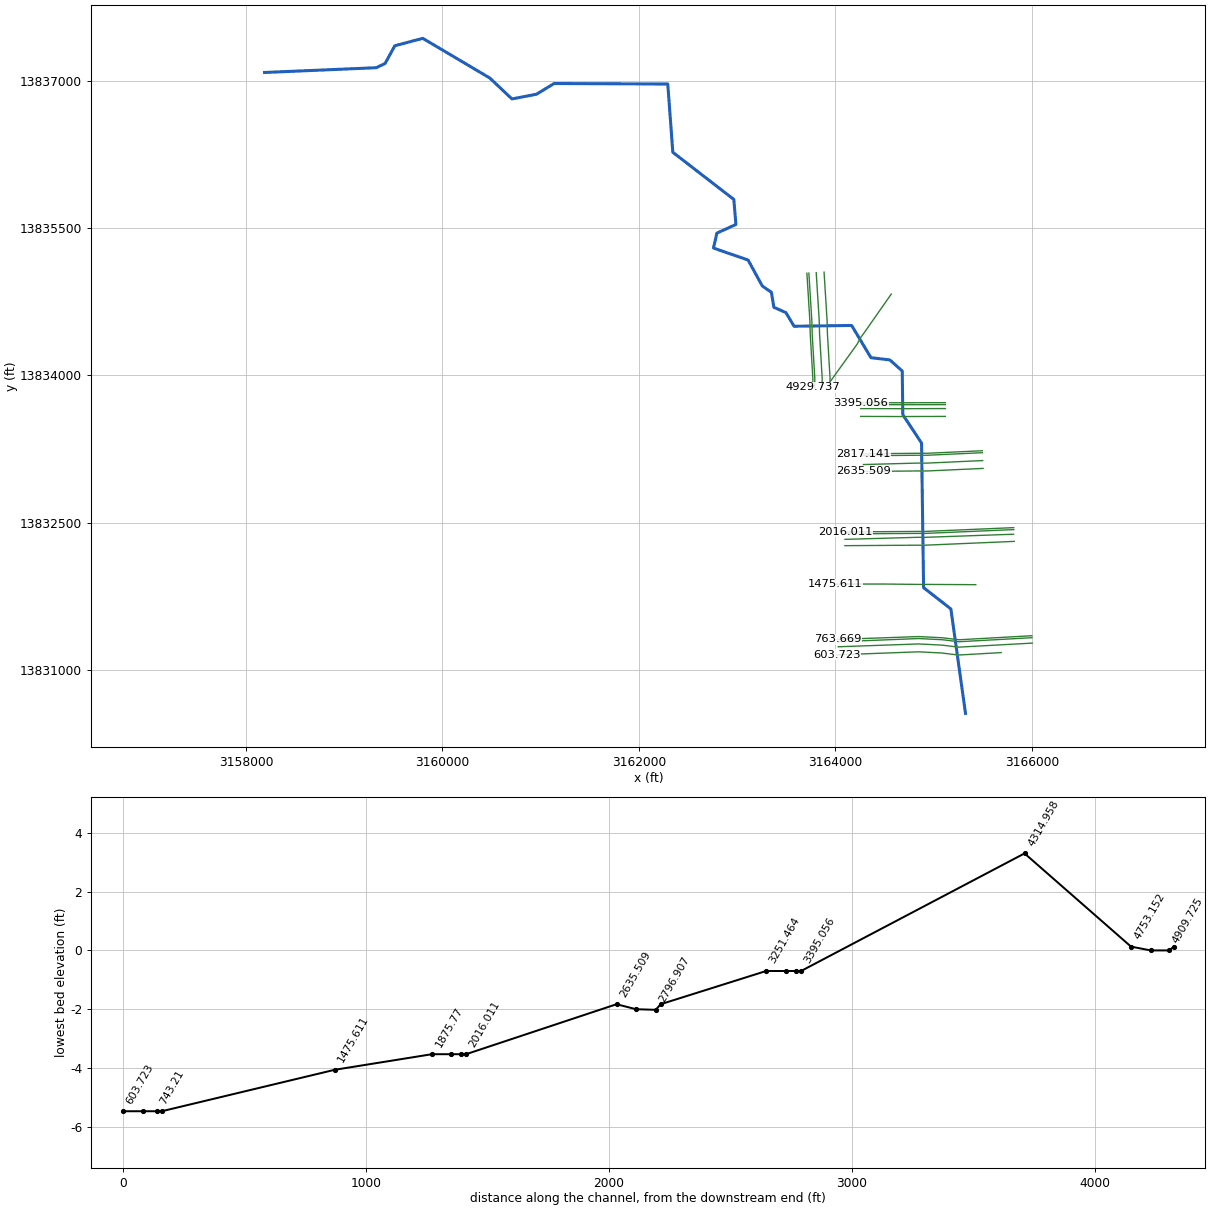
--- G112_00_00.prj (project) ---

Proj Title=G112-00-00
Current Plan=p04
Default Exp/Contr=.3,.1
English Units
Geom File=g01
Geom File=g02
Flow File=f05
Flow File=f06
Plan File=p04
Plan File=p05
Y Axis Title=Elevation
X Axis Title(PF)=Main Channel Distance
X Axis Title(XS)=Station
BEGIN DESCRIPTION:
San Jacinto
Panther Creek
HCFCD Unit G112-00-00
Flood Hazard Model
10, 2, 1, 0.2% Event
Filename G112_00_00.prj
Prepared by: Matthew Fischer Date: 5-25-04
Reviewd by:		Date:
Status Final Submittal
END DESCRIPTION:
DSS Export Rating Curves= 0
DSS Export Rating Curve Sorted= 0
DSS Export Volume Flow Curves= 0
DXF OffsetX= 0
DXF OffsetY= 0
DXF ScaleX= 1
DXF ScaleY= 10

--- G112_00_00.p04 (plan) ---

Plan Title=FEMA Effective June 2007
Version=Version 3.0.1  Mar 2001
Short Identifier=FEMAeff0607
Geom File=g01
Flow File=f05
Subcritical Flow
K Sum by GR= 0
Std Step Tol= 0.01
Critical Tol= 0.01
Num of Std Step Trials= 20
Max Error Tol= 0.3
Flow Tol Ratio= 0.001
Split Flow NTrial= 30
Split Flow Tol= 0.02
Split Flow Ratio= 0.02
Log Output Level= 0
Friction Slope Method= 0
Unsteady Friction Slope Method= 2
Secant Critical Depth
Global Vel Dist= 0 , 0 , 0
Global Log Level= 0
CheckData=True
Encroach Param=-1 ,0,0, 0
Computation Interval=1HOUR
Output Interval=1HOUR
Run HTab= 0
Run UNet= 0
Run PostProcess= 0
UNET Theta= 1
UNET ZTol= 0.02
UNET ZSATol= 0.1
UNET MxIter= 20
UNET MaxInSteps= 20
UNET DtIC= 0
UNET DtMin= 0
UNET MaxCRTS= 20
UNET WFStab= 2
UNET SFStab= 1
UNET WFX= 1
UNET SFX= 1
UNET Convert EG Bridges=-1
UNET Use Existing IB Tables=-1
Instantaneous Interval=1HOUR
Write IC File= 0
IC Time=0
Write Velocity= 0
Write Detailed= 0

--- G112_00_00.p05 (plan) ---

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Plan Title=Floodway
Short Identifier=Floodway0607
Geom File=g02
Flow File=f06
Encroach Param=-1 ,0,0, 2
Encroach River=G112-00-00
Encroach Reach=G112-00-00_0006
Encroach Node=4929.737
       1 4961.12 5028.88
Encroach Node=4909.725
       1 4961.12 5028.88
Encroach Node=4872
       1 4961.12 5033.88
Encroach Node=4834.382
       1 4966.12 5033.88
Encroach Node=4753.152
       1 4966.12 5033.88
Encroach Node=4314.958
       1 4966.88 5033.12
Encroach Node=3395.056
       1 4965.74 5023.94
Encroach Node=3374.958
       1 4970.74 5028.94
Encroach Node=3354
       1 4970.74 5028.94
Encroach Node=3334.509
       1 4970.74 5028.94
Encroach Node=3251.464
       1 4970.74 5028.94
Encroach Node=2817.141
       1 4816.07 5075.21
Encroach Node=2796.907
       1 4820.76 5075.21
Encroach Node=2756
       1 4820.76 5083.92
Encroach Node=2715.809
       1 4874.81 5083.92
Encroach Node=2635.509
       1 4820.76  5081.9
Encroach Node=2016.011
       1  4949.1 5052.04
Encroach Node=1995.995
       1  4949.1 5052.04
Encroach Node=1975
       1  4949.1 5052.04
Encroach Node=1955.945
       1  4949.1 5052.04
Encroach Node=1875.77
       1  4949.1    5051
Encroach Node=1475.611
       1 4979.74 5020.26
Encroach Node=763.669
       1 4916.09 5083.91
Encroach Node=743.21
       1 4906.99 5130.69
Encroach Node=715
       1 4906.99  5089.1
Encroach Node=686.91
       1 4906.99  5089.1
Encroach Node=603.723
       1    4923 5083.91

--- G112_00_00.f05 (steady flow) ---

Flow Title=FEMA Effective June 2007
Version=Version 3.0.1  Mar 2001
Number of Profiles= 4
Profile Names=10PCT_10yr, 2PCT_50yr, 1PCT_100yr, 0.2PCT_500yr
River Rch & RM=G112-00-00,G112-00-00_0006      ,4929.737
    1431    1993    2303    3096
River Rch & RM=G112-00-00,G112-00-00_0006      ,4314.958
    1478    2057    2378    3196
River Rch & RM=G112-00-00,G112-00-00_0006      ,3395.056
    1508    2100    2428    3263
River Rch & RM=G112-00-00,G112-00-00_0006      ,2796.907
    1532    2132    2463    3313
River Rch & RM=G112-00-00,G112-00-00_0006      ,2635.509
    1625    2258    2606    3512
River Rch & RM=G112-00-00,G112-00-00_0006      ,2016.011
    1711    2375    2737    3695
River Rch & RM=G112-00-00,G112-00-00_0006      ,1475.611
    1831    2537    2920    3951
River Rch & RM=G112-00-00,G112-00-00_0006      ,763.669
    1860    2575    2963    4010
Boundary for River Rch & Prof#=G112-00-00,G112-00-00_0006      , 1
Up Type= 0
Dn Type= 3
Dn Slope=.001517
DSS Import GetInterval= 0
DSS Import GetPeak= 0
DSS Import FillOption= 0

--- G112_00_00.f06 (steady flow) ---

Flow Title=Floodway
Version=Version 3.0.1  Mar 2001
Number of Profiles= 2
Profile Names=1PCT_100yr, 1PCTFloodway_100yrFW
River Rch & RM=G112-00-00,G112-00-00_0006      ,4929.737
    2303    2303
River Rch & RM=G112-00-00,G112-00-00_0006      ,4314.958
    2378    2378
River Rch & RM=G112-00-00,G112-00-00_0006      ,3395.056
    2428    2428
River Rch & RM=G112-00-00,G112-00-00_0006      ,2796.907
    2463    2463
River Rch & RM=G112-00-00,G112-00-00_0006      ,2635.509
    2606    2606
River Rch & RM=G112-00-00,G112-00-00_0006      ,2016.011
    2737    2737
River Rch & RM=G112-00-00,G112-00-00_0006      ,1475.611
    2920    2920
River Rch & RM=G112-00-00,G112-00-00_0006      ,763.669
    2963    2963
Boundary for River Rch & Prof#=G112-00-00,G112-00-00_0006      , 1
Up Type= 0
Dn Type= 3
Dn Slope=.001517
DSS Import GetInterval= 0
DSS Import GetPeak= 0
DSS Import FillOption= 0

--- G112_00_00.g01 (geometry) ---

Geom Title=G112-00-00 June 2007
Version=Version 3.0.1  Mar 2001

River Reach=G112-00-00   ,G112-00-00_0006
Reach XY= 30
     3158189.345    13837083.344        3159327.       13837132.
       3159416.5       13837175.      3159514.75       13837355.
      3159799.75       13837431.      3160480.75       13837028.
      3160707.75       13836814.        3160957.       13836862.
        3161137.       13836971.        3162294.       13836966.
       3162345.5       13836271.       3162966.5       13835791.
      3162987.75       13835536.        3162794.       13835448.
       3162759.5       13835296.      3163111.75       13835174.
      3163256.25       13834910.       3163348.5       13834846.
       3163374.5       13834693.      3163496.75       13834639.
      3163579.75       13834500.        3164166.       13834508.
       3164362.5       13834180.        3164555.       13834157.
        3164681.       13834044.      3164686.75       13833600.
       3164877.5       13833311.      3164898.25       13831839.
        3165176.       13831622.        3165325.       13830559.

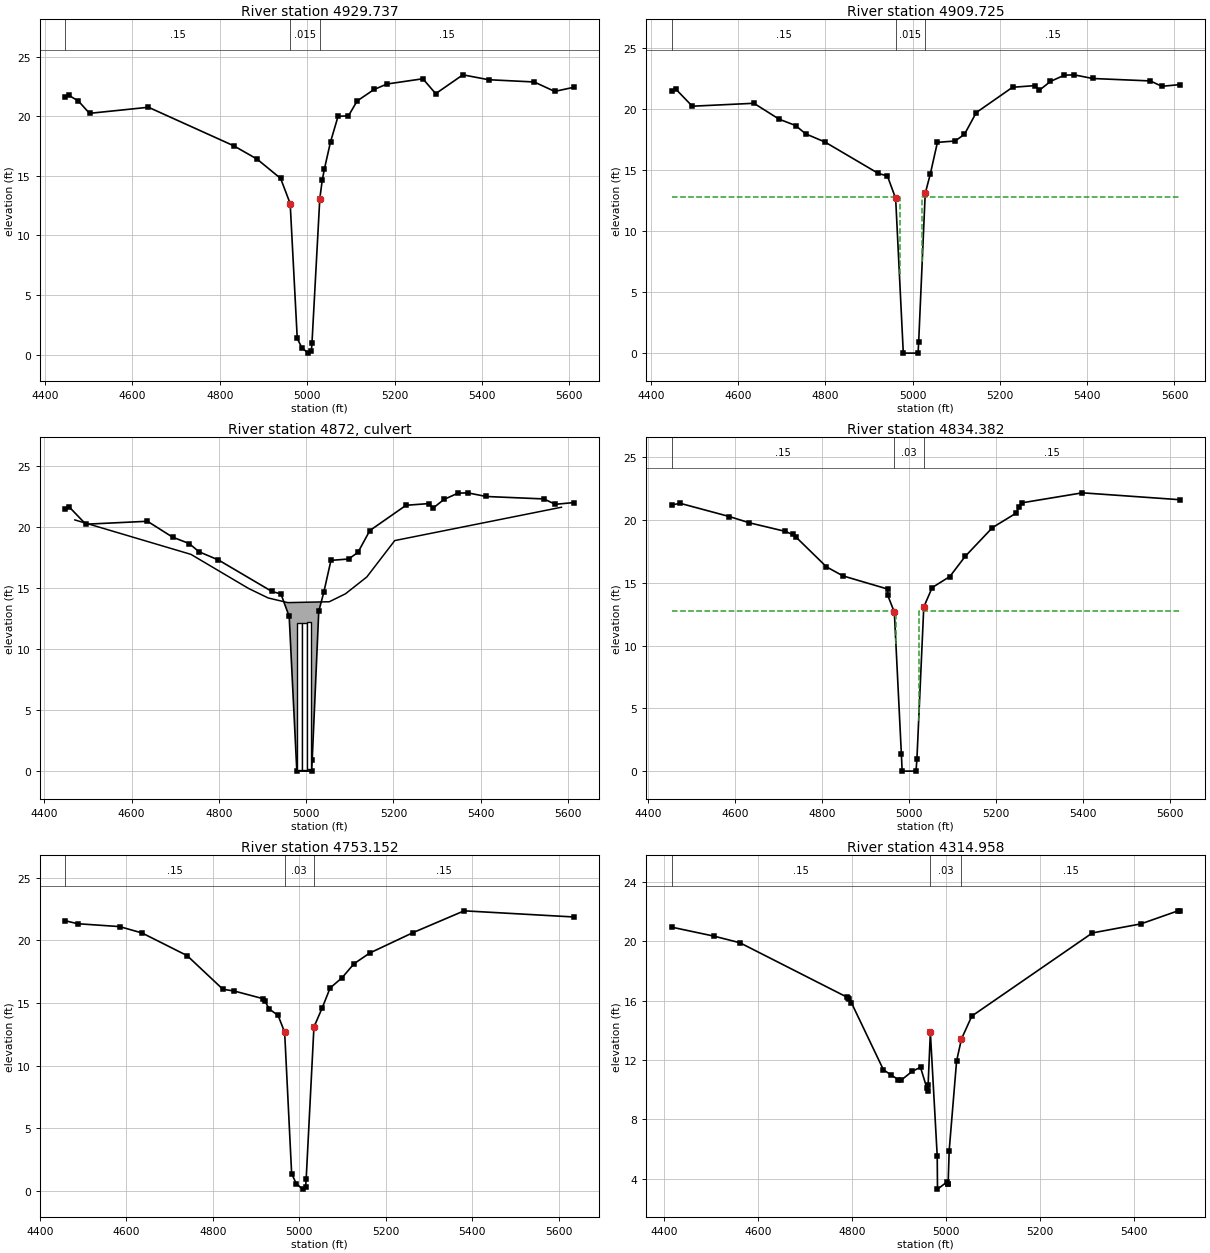
Type RM Length L Ch R = 1 ,4929.737,20,20.01,20.09
BEGIN DESCRIPTION:
Holland Ave
END DESCRIPTION:
XS GIS Cut Line= 6
     3163710.331    13835039.753     3163741.014    13834550.064
     3163743.916    13834436.532     3163743.916    13834426.352
     3163770.935    13833967.172     3163769.909    13833878.307
#Sta/Elev= 30
  4446.3   21.65 4454.62   21.75 4476.54   21.27 4501.96   20.24 4636.82   20.75
 4831.86   17.52 4885.04   16.41  4939.3   14.78 4961.12   12.67  4977.3    1.36
    4988     .57 5002.44     .13 5009.69     .32 5010.95     .94 5028.88   13.08
  5034.5   14.63 5039.54   15.59  5053.4   17.84 5070.68   19.99 5094.48   20.03
 5114.42   21.28 5153.04   22.24 5182.74    22.7 5264.74   23.14 5294.14   21.89
 5356.32   23.47 5415.26   23.06 5519.56   22.87 5566.36   22.08 5609.54   22.42
#Mann= 3 ,-1 , 0
  4446.3     .15       0 4961.12    .015       0 5028.88     .15       0
Bank Sta=4961.12,5028.88
XS Rating Curve= 0
Exp/Cntr=.5,.3

Type RM Length L Ch R = 1 ,4909.725,75,75.34,75.34
BEGIN DESCRIPTION:
Holland Ave
END DESCRIPTION:
XS GIS Cut Line= 6
     3163730.292    13835041.003     3163760.998    13834550.945
     3163763.916    13834436.787     3163763.916     13834426.94
     3163790.942    13833967.645     3163789.907    13833878.076
#Sta/Elev= 30
 4447.92    21.5 4457.45   21.62 4495.11   20.22 4636.38   20.46 4693.98   19.16
 4731.78   18.64 4754.71   17.96 4799.06   17.29 4921.69   14.71 4942.19   14.51
 4961.12   12.67 4978.65       0 5012.51       0 5013.88     .92 5028.88   13.08
  5040.3   14.63 5056.83   17.26 5097.18   17.37 5118.68   17.91 5145.89    19.7
 5228.93   21.77 5281.55   21.91 5290.46   21.53 5315.88   22.25 5347.71   22.76
    5370   22.79  5412.5   22.49 5544.74   22.29  5570.9   21.85 5612.65   21.99
#Mann= 3 ,-1 , 0
 4447.92     .15       0 4961.12    .015       0 5028.88     .15       0
#XS Ineff= 2 , 0
       0    4970    12.8    5022       0    12.8
Permanent Ineff=
       F       F
Bank Sta=4961.12,5028.88
XS Rating Curve= 0
Exp/Cntr=.5,.3

Type RM Length L Ch R = 2 ,4872    ,,,
BEGIN DESCRIPTION:
Culverts at Holland Ave
END DESCRIPTION:
Bridge Culvert--1,0,-1,-1, 0
Deck Dist Width WeirC Skew NumUp NumDn MinLoCord MaxHiCord MaxSubmerge Is_Ogee
10,58,2.6,0, 10, 10, , , .95, 0, 0,0,,
    4470    4736    4868    4913    4958    5053    5090    5139    5203    5585
   20.57   17.75   14.96   14.18    13.8   13.87   14.52    15.9   18.88   21.61
       0       0       0       0       0       0       0       0       0       0
    4470    4736    4868    4913    4958    5053    5090    5139    5203    5585
   20.57   17.75   14.96   14.18    13.8   13.87   14.52    15.9   18.88   21.61
       0       0       0       0       0       0       0       0       0       0
BR Coef=-1 , 0 , 0 ,, 0 ,,,.8,-1,,0,
WSPro=,,,, 1 ,,,, 0 ,,,, 0 ,,,,-1 ,-1 ,-1 , 0 , 0 , 0 , 0 , 0
Culvert=2,12,10,58,.012,.5,1,10,1,.12,4985,.14,4989,Culvert #1  , 0 ,10
Culvert Bottom n=.012
Culvert=2,12,10,58,.012,.5,1,10,1,.12,4996,.14,5000,Culvert #2  , 0 ,10
Culvert Bottom n=.012
Culvert=2,12,10,58,.012,.5,1,10,1,.18,5007,.2,5011,Culvert #3  , 0 ,10
Culvert Bottom n=.012
BC Design=,, 0 ,, 0 ,,,,,,

Type RM Length L Ch R = 1 ,4834.382,80,81.23,80.36
BEGIN DESCRIPTION:
Holland Ave
END DESCRIPTION:
XS GIS Cut Line= 6
     3163805.145    13835045.694     3163835.939    13834554.249
     3163838.916    13834437.746     3163838.916    13834429.145
     3163865.967    13833969.416     3163864.902    13833877.209
#Sta/Elev= 26
 4453.48   21.22  4473.4   21.34 4586.24   20.29 4632.38   19.79 4714.82   19.11
 4731.68   18.86 4740.66   18.62  4809.9   16.28 4847.76   15.56 4950.68   14.51
 4950.93   14.01 4966.12   12.67  4982.3    1.36 4984.08       0 5015.97       0
 5018.05     .93 5033.88   13.08 5053.22   14.63 5093.92   15.51 5129.08   17.11
 5192.08   19.41 5246.98   20.57 5252.78   21.06  5259.3   21.38 5398.92   22.18
 5623.76   21.63
#Mann= 3 ,-1 , 0
 4453.48     .15       0 4966.12     .03       0 5033.88     .15       0
#XS Ineff= 2 , 0
       0    4970    12.8    5022       0    12.8
Permanent Ineff=
       F       F
Bank Sta=4966.12,5033.88
XS Rating Curve= 0
Exp/Cntr=.5,.3

Type RM Length L Ch R = 1 ,4753.152,499.79,438.19,257.7
BEGIN DESCRIPTION:
Holland Ave
END DESCRIPTION:
XS GIS Cut Line= 6
     3163884.989    13835050.696     3163915.875    13834557.774
     3163918.916    13834438.768     3163918.916    13834431.496
     3163945.995    13833971.306     3163944.897    13833876.286
#Sta/Elev= 26
 4458.35   21.58 4486.87   21.34 4584.17   21.11 4636.13    20.6 4740.45   18.79
 4823.27    16.1 4849.59   15.96 4914.93   15.36 4920.48   15.16 4930.28   14.53
 4950.93   14.01 4966.12   12.67  4982.3    1.36    4993     .57 5007.44     .13
 5014.69     .32 5015.95     .94 5033.88   13.08 5053.22   14.63 5071.28    16.2
 5099.44   17.04 5126.53   18.14 5163.14      19 5262.67   20.62 5381.46   22.37
 5634.57   21.88
#Mann= 3 ,-1 , 0
 4458.35     .15       0 4966.12     .03       0 5033.88     .15       0
Bank Sta=4966.12,5033.88
XS Rating Curve= 0
Exp/Cntr=.3,.1

Type RM Length L Ch R = 1 ,4314.958,1067.17,919.9,556.47
XS GIS Cut Line= 5
     3164568.937    13834827.259     3164300.823    13834443.858
     3164252.397    13834377.667     3164222.528    13834318.538
     3163950.114    13833939.956
#Sta/Elev= 30
 4415.98   20.95 4506.76   20.34 4561.16    19.9  4788.3   16.25 4791.04   16.21
 4794.38   16.13 4798.86   15.85 4866.94   11.34 4883.84   10.98 4898.98   10.67
 4904.22   10.63 4928.38   11.24 4945.88   11.51 4959.62   10.08    4962    9.91
  4962.1   10.34 4966.88   13.86 4981.48    5.53 4982.07     3.3 5001.95    3.77
 5003.47    3.63 5004.69    3.62 5006.95     5.9 5022.74   11.93 5033.12   13.42
 5055.19   14.96 5311.88   20.56 5415.22   21.17 5494.28   22.05  5498.5   22.04
#Mann= 3 ,-1 , 0
 4415.98     .15       0 4966.88     .03       0 5033.12     .15       0
Bank Sta=4966.88,5033.12
XS Rating Curve= 0
Exp/Cntr=.3,.1

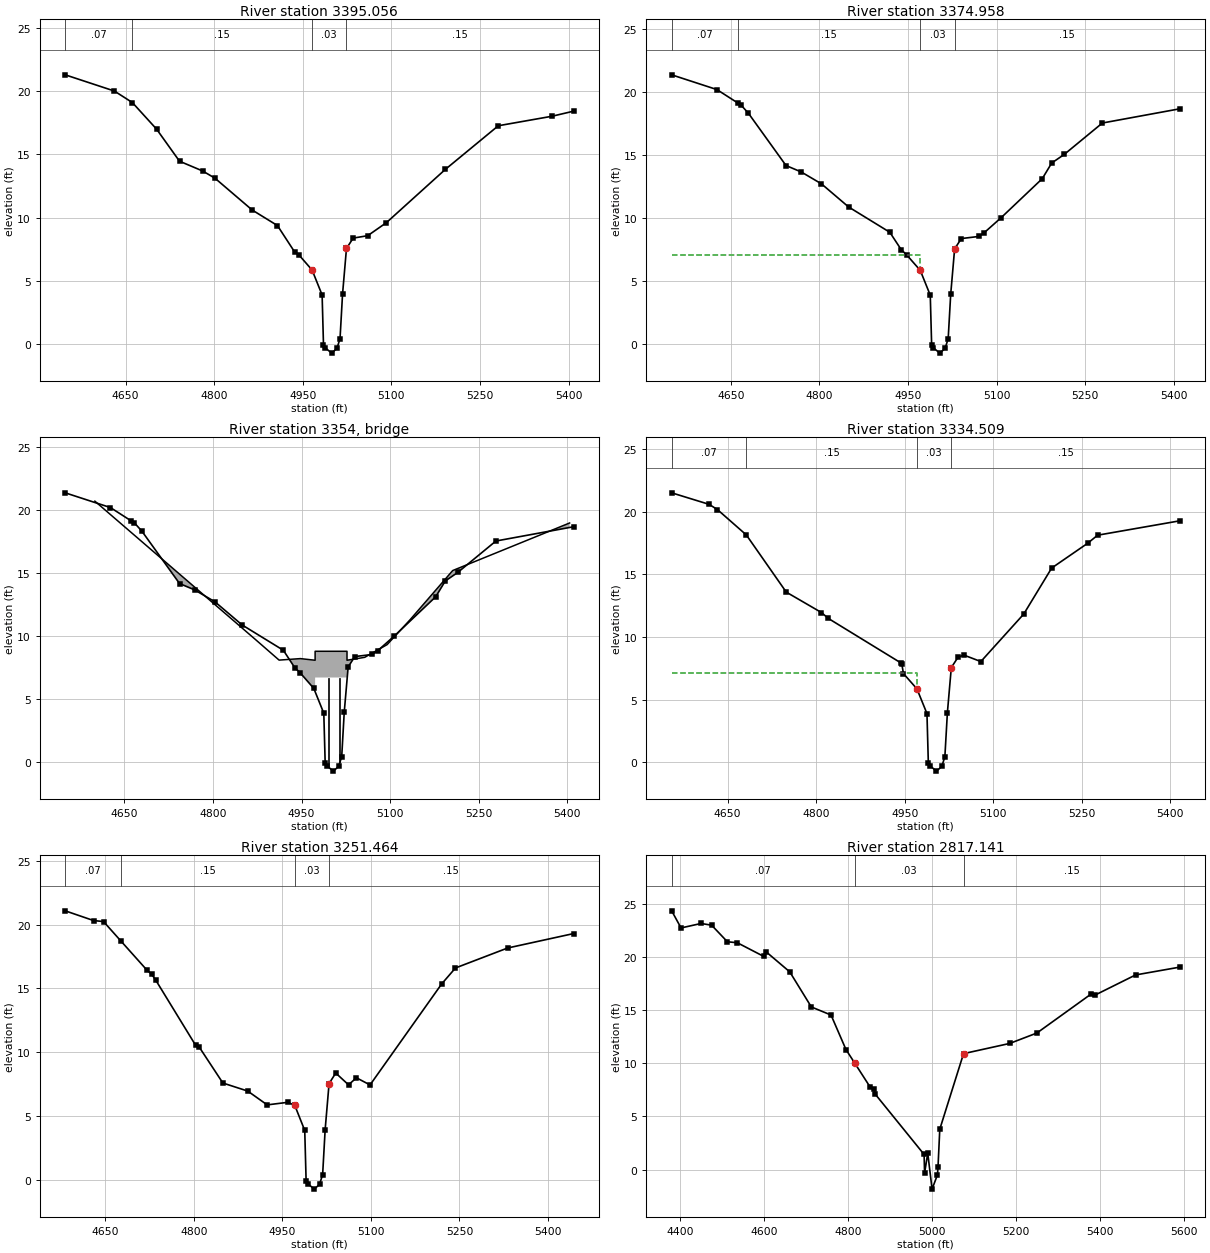
Type RM Length L Ch R = 1 ,3395.056,21.41,20.1,20.54
BEGIN DESCRIPTION:
2nd Street
END DESCRIPTION:
XS GIS Cut Line= 4
     3165119.402    13833722.072     3164766.011    13833721.083
     3164599.447    13833721.083     3164258.631    13833722.072
#Sta/Elev= 27
 4547.66   21.27 4630.96   19.99  4661.4   19.08 4702.42   16.98 4741.24   14.45
 4780.38   13.68 4801.24   13.11 4864.22    10.6 4907.06    9.37 4936.24    7.28
 4942.89    7.08 4965.74    5.86  4982.7    3.89 4985.02    -.03 4987.72    -.27
 4998.85     -.7 5007.73    -.33 5013.03     .44  5017.3    3.96 5023.94    7.56
 5035.27    8.38 5059.88    8.57 5091.56     9.6 5191.24    13.8 5281.04   17.25
 5371.98      18 5408.44    18.4
#Mann= 4 ,-1 , 0
 4547.66     .07       0  4661.4     .15       0 4965.74     .03       0
 5023.94     .15       0
Bank Sta=4965.74,5023.94
XS Rating Curve= 0
Exp/Cntr=.5,.3

Type RM Length L Ch R = 1 ,3374.958,42.97,40.45,41.08
BEGIN DESCRIPTION:
2nd Street
END DESCRIPTION:
XS GIS Cut Line= 6
     3165119.458    13833702.072     3164766.039    13833701.083
     3164695.568    13833701.083     3164642.118    13833701.083
     3164599.418    13833701.083     3164258.573    13833702.072
#Sta/Elev= 30
 4549.76   21.36 4626.44   20.19 4661.68   19.13 4666.88   18.98 4679.64   18.32
 4743.38   14.17 4769.22   13.66 4803.38   12.72 4849.28   10.89  4919.2    8.88
 4938.38    7.51 4947.89    7.08 4970.74    5.86  4987.7    3.89 4990.02    -.03
 4992.72    -.27 5003.85     -.7 5012.73    -.33 5018.03     .44  5022.3    3.96
 5028.94    7.56 5040.27    8.38 5070.04    8.55  5079.4    8.86 5107.36   10.02
  5177.4   13.13 5193.38   14.37 5214.58   15.05 5279.18   17.54 5410.64   18.67
#Mann= 4 ,-1 , 0
 4549.76     .07       0 4661.68     .15       0 4970.74     .03       0
 5028.94     .15       0
#XS Ineff= 2 , 0
       0 4970.74     7.1 5028.94       0    7.56
Permanent Ineff=
       F       F
Bank Sta=4970.74,5028.94
XS Rating Curve= 0
Exp/Cntr=.5,.3

Type RM Length L Ch R = 3 ,3354    ,,,
BEGIN DESCRIPTION:
Bridge at 2nd St
END DESCRIPTION:
Bridge Culvert--1,0,-1,-1, 0
Deck Dist Width WeirC Skew NumUp NumDn MinLoCord MaxHiCord MaxSubmerge Is_Ogee
3,28,2.6,0, 14, 14, , , .95, 0, 0,0,,
    4600    4872    4912    4948    4973    4973    5006    5027    5027    5057
    5095    5134    5206    5404
    20.7    9.73     8.1    8.22    8.09     8.8     8.8     8.8    8.09    8.32
    9.33   11.31    15.2   18.97
               0       0       0       0    6.72    6.72    6.72       0       0
       0       0       0       0
    4600    4872    4912    4948    4973    4973    5006    5027    5027    5057
    5095    5134    5206    5404
    20.7    9.73     8.1    8.22    8.09     8.8     8.8     8.8    8.09    8.32
    9.33   11.31    15.2   18.97
               0       0       0       0    6.72    6.72    6.72       0       0
       0       0       0       0
Pier Skew, UpSta & Num, DnSta & Num=  ,4995, 4 ,4995, 4 , 3 , 3 , 0 ,,
     1.2     1.2     1.9     1.9
      -5    4.82    4.82       7
     1.2     1.2     1.9     1.9
      -5    4.82    4.82       7
Pier Skew, UpSta & Num, DnSta & Num=  ,5015, 4 ,5015, 4 , 3 , 3 , 0 ,,
     1.2     1.2     1.9     1.9
      -5    4.82    4.82       7
     1.2     1.2     1.9     1.9
      -5    4.82    4.82       7
BR Coef=-1 , 1 , 0 ,, 0 ,,,.8,0,2,0,
WSPro=,,,, 1 ,,,, 0 ,,,, 0 ,,,,-1 ,-1 ,-1 , 0 , 0 , 0 , 0 , 0
BC Design=,, 0 ,, 0 ,,,,,,

Type RM Length L Ch R = 1 ,3334.509,86.42,83.05,82.15
BEGIN DESCRIPTION:
2nd Street
END DESCRIPTION:
XS GIS Cut Line= 4
      3165119.57    13833662.072     3164766.095    13833661.083
      3164599.36    13833661.083     3164258.457    13833662.072
#Sta/Elev= 27
 4555.24    21.5 4618.72   20.58 4632.86   20.16 4681.72   18.14 4749.36   13.58
 4808.98   11.95 4820.66   11.48 4943.98    7.92  4945.2    7.81 4947.89    7.08
 4970.74    5.86  4987.7    3.89 4990.02    -.03 4992.72    -.27 5003.85     -.7
 5012.73    -.33 5018.03     .44  5022.3    3.96 5028.94    7.56 5040.27    8.38
 5050.06    8.56 5078.98    8.04 5151.66   11.83 5198.98    15.5 5260.06   17.48
 5276.78   18.12 5416.36   19.27
#Mann= 4 ,-1 , 0
 4555.24     .07       0 4681.72     .15       0 4970.74     .03       0
 5028.94     .15       0
#XS Ineff= 2 , 0
       0 4970.74     7.1 5028.94       0    7.56
Permanent Ineff=
       F       F
Bank Sta=4970.74,5028.94
XS Rating Curve= 0
Exp/Cntr=.5,.3

Type RM Length L Ch R = 1 ,3251.464,417.12,434.32,385.82
BEGIN DESCRIPTION:
2nd Street
END DESCRIPTION:
XS GIS Cut Line= 4
     3165119.794    13833582.072     3164766.207    13833581.083
     3164599.244    13833581.083     3164258.225    13833582.072
#Sta/Elev= 30
 4581.71   21.07 4629.72   20.31 4646.66   20.23 4676.48   18.69 4719.89   16.45
 4728.44    16.1 4735.15   15.65 4802.76   10.55 4809.17   10.39 4848.95     7.6
 4891.09    6.97 4924.06    5.89  4958.8    6.09 4970.74    5.86  4987.7    3.89
 4990.02    -.03 4992.72    -.27 5003.85     -.7 5012.73    -.33 5018.03     .44
  5022.3    3.96 5028.94    7.56 5040.27    8.38 5061.89    7.46 5075.33    8.01
 5098.36    7.45 5219.76   15.35 5243.16    16.6 5331.46   18.16 5443.28   19.29
#Mann= 4 ,-1 , 0
 4581.71     .07       0 4676.48     .15       0 4970.74     .03       0
 5028.94     .15       0
Bank Sta=4970.74,5028.94
XS Rating Curve= 0
Exp/Cntr=.3,.1

Type RM Length L Ch R = 1 ,2817.141,20.13,20.23,20.36
BEGIN DESCRIPTION:
Clinton Drive
END DESCRIPTION:
XS GIS Cut Line= 4
     3165495.639    13833232.604     3164933.198    13833206.753
     3164827.945    13833206.753     3164286.219    13833201.595
#Sta/Elev= 30
 4380.46   24.34 4402.74   22.73 4450.31   23.15 4475.55   22.99 4513.11   21.43
 4536.66   21.34 4599.29   20.06 4605.51   20.48 4661.57    18.6 4712.94    15.3
 4759.84   14.54 4795.43   11.29 4816.07   10.03 4853.51    7.73  4862.3    7.59
 4864.81    7.11 4981.34    1.43 4982.49    -.33 4990.05    1.55 5000.34   -1.83
 5013.09    -.49 5014.43     .21 5018.66     3.8 5075.21   10.91 5185.16   11.87
 5249.89   12.85 5379.38   16.53 5388.94   16.43 5484.72   18.31  5590.5   19.05
#Mann= 3 ,-1 , 0
 4380.46     .07       0 4816.07     .03       0 5075.21     .15       0
Bank Sta=4816.07,5075.21
XS Rating Curve= 0
Exp/Cntr=.5,.3

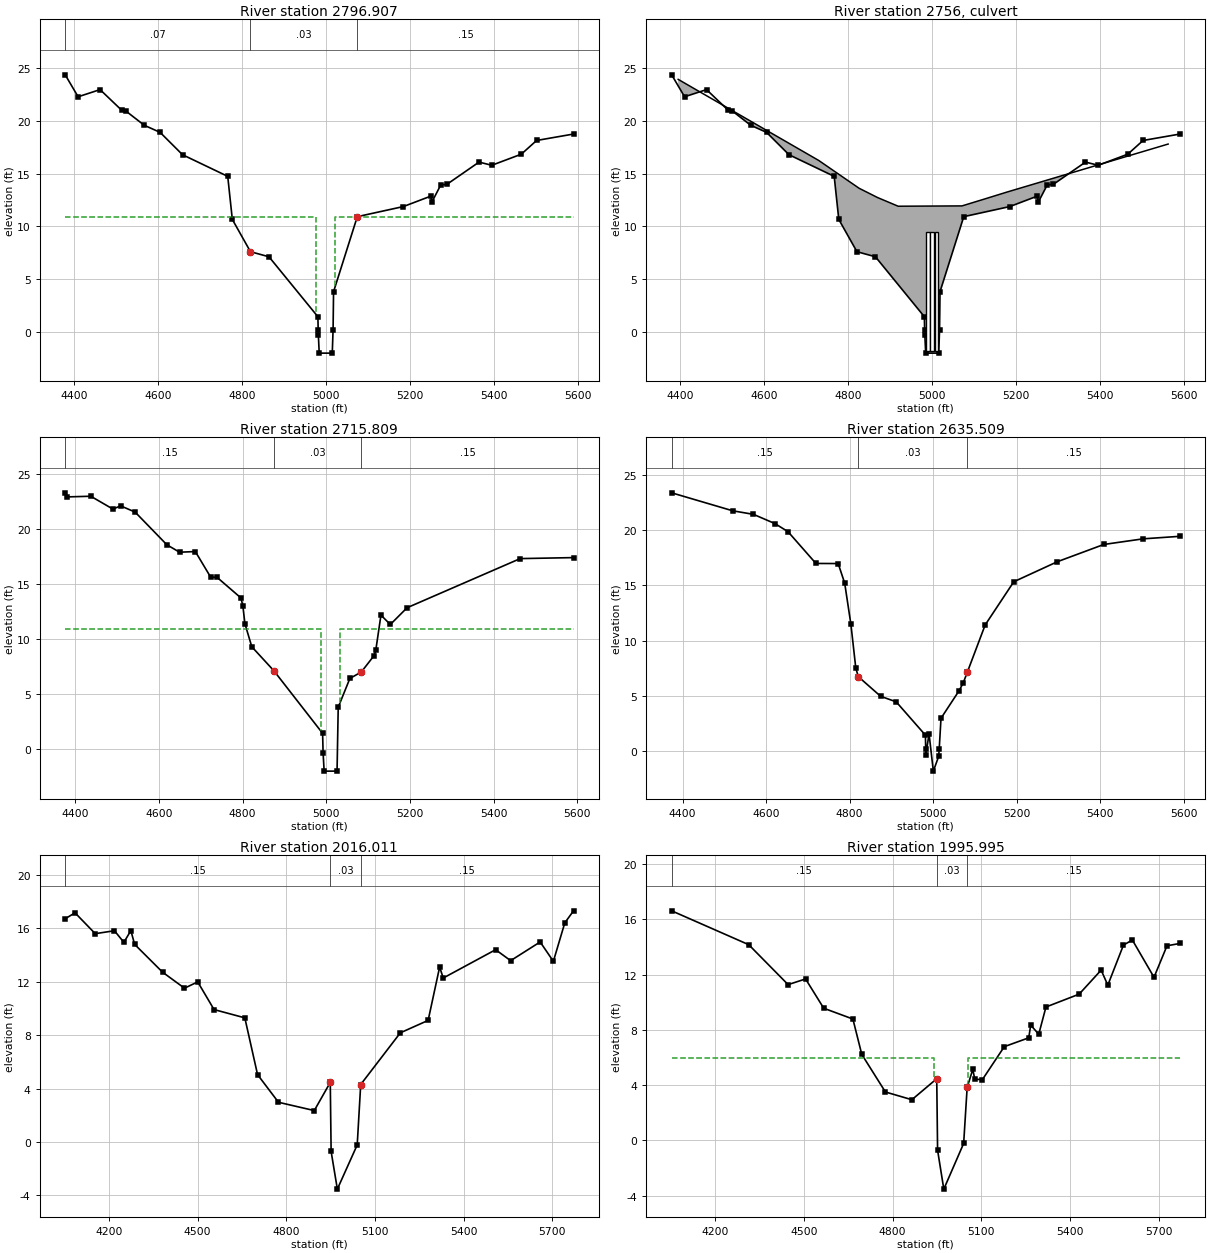
Type RM Length L Ch R = 1 ,2796.907,80.51,81.1,86.39
BEGIN DESCRIPTION:
Clinton Drive
END DESCRIPTION:
XS GIS Cut Line= 4
     3165496.558    13833212.625     3164933.657    13833186.753
     3164828.041    13833186.753     3164286.409    13833181.596
#Sta/Elev= 30
 4379.48   24.35 4410.24   22.27 4462.52   22.95  4514.1   20.99 4524.34   20.91
 4567.72   19.57 4605.46    18.9  4658.9   16.78 4766.58   14.73 4777.52   10.65
 4820.76    7.59 4864.81    7.11 4981.34    1.43    4982     .21 4982.49    -.33
 4984.51   -2.02 5015.59   -2.02 5017.54     .21 5018.66     3.8 5075.21   10.91
 5185.16   11.87 5249.89   12.85 5252.92    12.3  5273.8    13.9 5288.88   13.98
 5365.14   16.08 5395.58   15.78 5465.86   16.83 5502.32   18.13 5590.26   18.74
#Mann= 3 ,-1 , 0
 4379.48     .07       0 4820.76     .03       0 5075.21     .15       0
#XS Ineff= 2 , 0
       0    4977    10.9    5023       0    10.9
Permanent Ineff=
       F       F
Bank Sta=4820.76,5075.21
XS Rating Curve= 0
Exp/Cntr=.5,.3

Type RM Length L Ch R = 2 ,2756    ,,,
BEGIN DESCRIPTION:
Culverts at Clinton Drive
END DESCRIPTION:
Bridge Culvert--1,0,-1,-1, 0
Deck Dist Width WeirC Skew NumUp NumDn MinLoCord MaxHiCord MaxSubmerge Is_Ogee
8,54,2.6,0, 9, 9, , , .95, 0, 0,0,,
    4395    4730    4826    4870    4919    5071    5122    5178    5562
   23.92   16.23    13.6   12.72    11.9   11.93   12.55   13.24   17.79
      -5      -5      -5      -5      -5      -5      -5      -5      -5
    4395    4730    4826    4870    4919    5071    5122    5178    5562
   23.92   16.23    13.6   12.72    11.9   11.93   12.55   13.24   17.79
      -5      -5      -5      -5      -5      -5      -5      -5      -5
BR Coef=-1 , 0 , 0 ,, 0 ,,,.8,-1,,0,
WSPro=,,,, 1 ,,,, 0 ,,,, 0 ,,,,-1 ,-1 ,-1 , 0 , 0 , 0 , 0 , 0
Culvert=2,11.3,9.3,54,.012,.5,1,10,1,-1.82,4989.7,-1.73,4999.7,Culvert #1  , 0 ,8
Culvert Bottom n=.012
Culvert=2,11.3,9.3,54,.012,.5,1,10,1,-1.82,5000,-1.73,5010,Culvert #2  , 0 ,8
Culvert Bottom n=.012
Culvert=2,11.3,9.3,54,.012,.5,1,10,1,-1.82,5010.3,-1.73,5020.3,Culvert #3  , 0 ,8
Culvert Bottom n=.012
BC Design=,, 0 ,, 0 ,,,,,,

Type RM Length L Ch R = 1 ,2715.809,80.29,80.3,74.92
BEGIN DESCRIPTION:
Clinton Drive
END DESCRIPTION:
XS GIS Cut Line= 4
     3165500.231    13833132.709     3164935.495    13833106.753
     3164828.422    13833106.753     3164285.482    13833092.136
#Sta/Elev= 30
 4375.82   23.26 4380.23   22.89 4436.99   22.95 4490.11   21.78 4508.22   22.08
 4543.07   21.51 4618.76   18.55 4649.24   17.87    4687   17.93  4723.6   15.61
 4738.93   15.59 4796.03   13.72 4800.67      13 4805.54   11.38    4822    9.29
 4874.81    7.11 4991.34    1.43 4992.49    -.33 4994.98      -2 5025.88      -2
 5028.66     3.8 5056.52    6.41 5083.92       7 5114.48    8.49 5118.69    9.02
 5130.85   12.16 5153.31   11.31  5193.3   12.83 5463.84   17.29 5591.36   17.38
#Mann= 3 ,-1 , 0
 4375.82     .15       0 4874.81     .03       0 5083.92     .15       0
#XS Ineff= 2 , 0
       0    4987    10.9    5033       0    10.9
Permanent Ineff=
       F       F
Bank Sta=4874.81,5083.92
XS Rating Curve= 0
Exp/Cntr=.5,.3

Type RM Length L Ch R = 1 ,2635.509,615.12,619.5,616.83
BEGIN DESCRIPTION:
Clinton Drive
END DESCRIPTION:
XS GIS Cut Line= 4
     3165503.904    13833052.794     3164937.332    13833026.753
     3164828.802    13833026.753     3164287.933    13833021.603
#Sta/Elev= 30
 4374.06   23.39 4520.32   21.76 4569.82   21.44 4621.34    20.6 4652.48   19.87
  4719.3   16.99 4772.56   16.98 4788.12   15.21    4803   11.48  4814.7    7.51
 4820.76    6.73  4874.2    4.95 4911.43    4.45 4981.34    1.43    4982     .21
 4982.49    -.33 4990.05    1.55 5000.34   -1.83 5013.09    -.49 5014.43     .21
 5018.66    2.96  5061.8    5.45  5071.8    6.16  5081.9    7.16  5124.4   11.42
  5192.8   15.33 5297.28   17.15 5408.22   18.71 5502.28   19.22 5590.66   19.45
#Mann= 3 ,-1 , 0
 4374.06     .15       0 4820.76     .03       0  5081.9     .15       0
Bank Sta=4820.76,5081.9
XS Rating Curve= 0
Exp/Cntr=.3,.1

Type RM Length L Ch R = 1 ,2016.011,20.01,20.02,20.41
BEGIN DESCRIPTION:
Railroad
END DESCRIPTION:
XS GIS Cut Line= 5
 3165815.598788413832449.8200756     3165747.661    13832446.912
     3164912.104    13832411.146     3164826.762    13832411.146
 3164097.039486213832406.2767375
#Sta/Elev= 30
 4052.52   16.71 4085.78   17.15 4154.06   15.59  4219.1   15.81 4250.96   14.94
 4274.56   15.82 4287.36   14.79 4381.72   12.71 4455.94   11.51 4500.76   11.98
 4555.98    9.91 4660.06    9.29 4703.14    5.04 4773.88    2.97    4895    2.35
  4949.1    4.46 4951.97    -.71 4973.04   -3.53 5040.23    -.22 5052.04     4.3
 5186.12    8.17 5280.14     9.1 5318.98   13.09  5331.2   12.27  5508.4   14.39
 5559.22   13.57 5659.02   14.97 5703.72   13.52 5742.36    16.4 5771.92    17.3
#Mann= 3 ,-1 , 0
 4052.52     .15       0  4949.1     .03       0 5052.04     .15       0
Bank Sta=4949.1,5052.04
XS Rating Curve= 0
Exp/Cntr=.5,.3

Type RM Length L Ch R = 1 ,1995.995,42.99,40.05,46.15
BEGIN DESCRIPTION:
Railroad
END DESCRIPTION:
XS GIS Cut Line= 5
   3165816.4550313832429.8391412     3165748.517    13832426.931
     3164912.532    13832391.146     3164826.829    13832391.146
 3164097.173486513832386.2776904
#Sta/Elev= 30
 4052.16   16.61  4312.9   14.16 4446.16   11.27 4505.28   11.68  4566.7    9.56
  4665.4    8.78 4695.44    6.22 4775.46     3.5    4865    2.94  4949.1    4.46
 4951.97    -.71 4973.04   -3.53 5040.23    -.22 5052.04    3.83    5071    5.13
    5078    4.42  5103.7     4.4  5177.7    6.78 5260.42    7.42 5267.12    8.34
  5294.3    7.68  5318.7    9.65 5431.02   10.58 5505.44   12.32    5528   11.23
 5580.92   14.13 5611.02    14.5 5684.34    11.8 5728.26   14.08 5772.28   14.25
#Mann= 3 ,-1 , 0
 4052.16     .15       0  4949.1     .03       0 5052.04     .15       0
#XS Ineff= 2 , 0
     -68    4940    5.95    5054     -68    5.95
Permanent Ineff=
       F       F
Bank Sta=4949.1,5052.04
XS Rating Curve= 0
Exp/Cntr=.5,.3

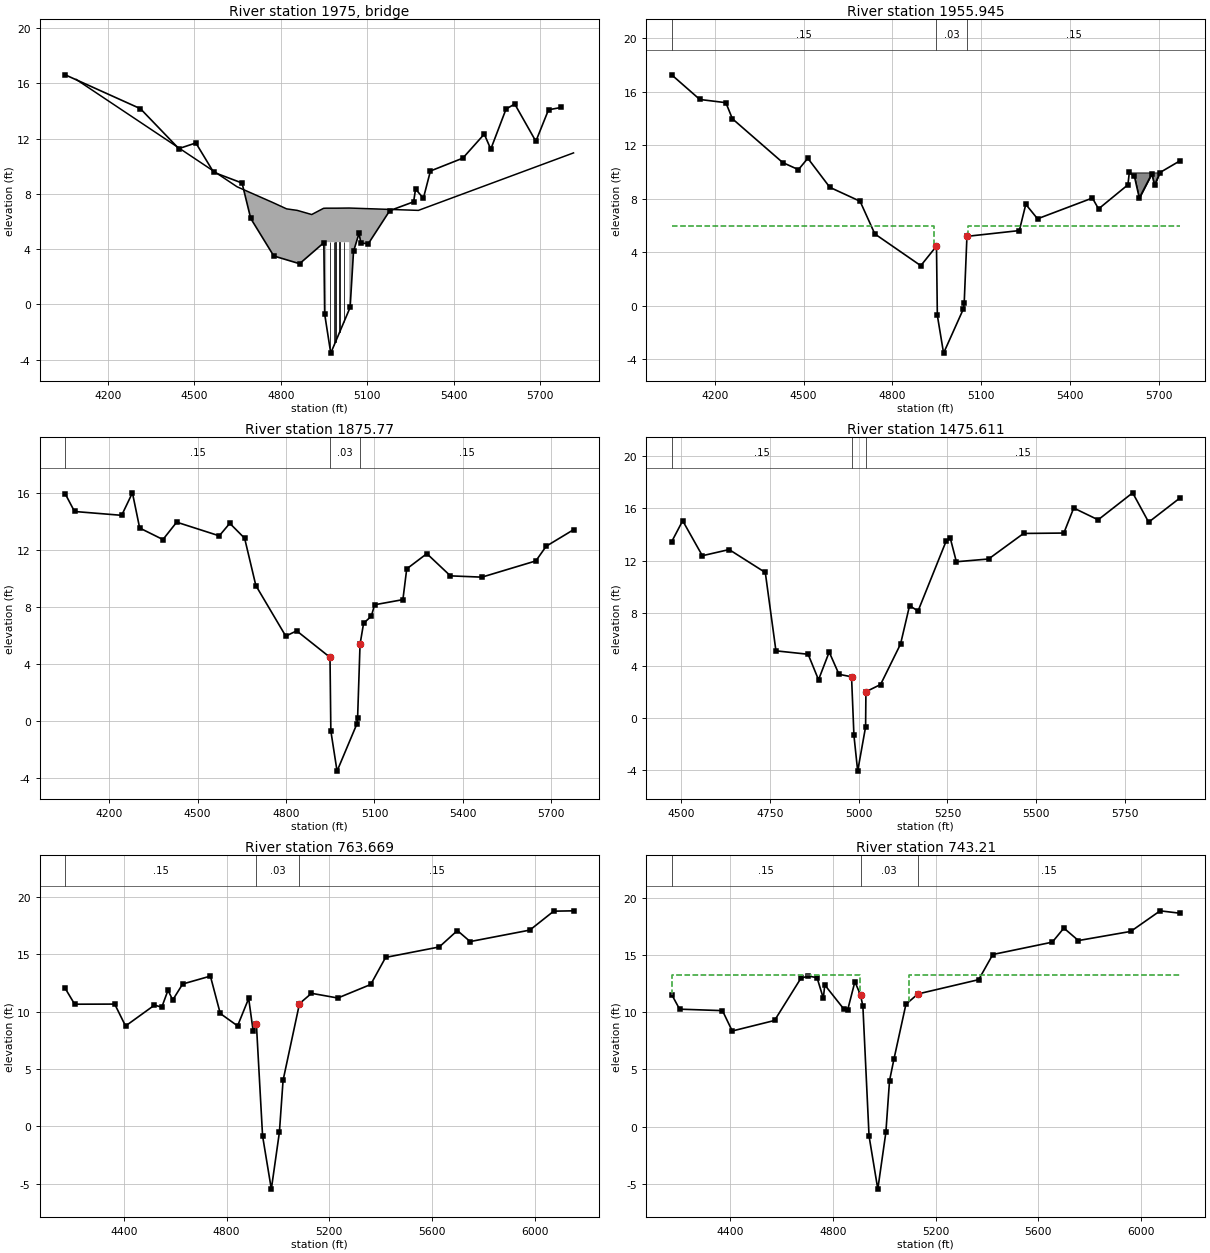
Type RM Length L Ch R = 3 ,1975    ,,,
BEGIN DESCRIPTION:
Railroad Bridge
END DESCRIPTION:
Bridge Culvert--1,0,-1,-1, 0
Deck Dist Width WeirC Skew NumUp NumDn MinLoCord MaxHiCord MaxSubmerge Is_Ogee
17,15,2.6,0, 14, 14, , , .95, 0, 0,0,,
    4090    4648    4772    4820    4857    4907    4948    4957    4957    4994
    5037    5037    5277    5815
   16.28    8.51    7.37    6.91     6.8     6.5    6.95    6.96    6.96    6.96
    6.97    6.97     6.8   10.96
      -5      -5      -5      -5      -5      -5      -5      -5     4.5     4.5
     4.5      -5      -5      -5
    4090    4648    4772    4820    4857    4907    4948    4957    4957    4994
    5037    5037    5277    5815
   16.28    8.51    7.37    6.91     6.8     6.5    6.95    6.96    6.96    6.96
    6.97    6.97     6.8   10.96
      -5      -5      -5      -5      -5      -5      -5      -5     4.5     4.5
     4.5      -5      -5      -5
Pier Skew, UpSta & Num, DnSta & Num=  ,4970, 2 ,4970, 2 , 0 , 0 , 0 ,,
     1.5     1.5
      -5       5
     1.5     1.5
      -5       5
Pier Skew, UpSta & Num, DnSta & Num=  ,4985, 2 ,4985, 2 , 0 , 0 , 0 ,,
     1.5     1.5
      -5       5
     1.5     1.5
      -5       5
Pier Skew, UpSta & Num, DnSta & Num=  ,4990, 2 ,4990, 2 , 0 , 0 , 0 ,,
     1.5     1.5
      -5       5
     1.5     1.5
      -5       5
Pier Skew, UpSta & Num, DnSta & Num=  ,5004, 2 ,5004, 2 , 0 , 0 , 0 ,,
     1.5     1.5
      -5       5
     1.5     1.5
      -5       5
Pier Skew, UpSta & Num, DnSta & Num=  ,5019, 2 ,5019, 2 , 0 , 0 , 0 ,,
     1.5     1.5
      -5       5
     1.5     1.5
      -5       5
BR Coef=-1 , 1 , 0 ,, 0 ,,,.8,0,2,0,
WSPro=,,,, 1 ,,,, 0 ,,,, 0 ,,,,-1 ,-1 ,-1 , 0 , 0 , 0 , 0 , 0
BC Design=,, 0 ,, 0 ,,,,,,

Type RM Length L Ch R = 1 ,1955.945,77.05,80.18,76.31
BEGIN DESCRIPTION:
Railroad
END DESCRIPTION:
XS GIS Cut Line= 5
 3165814.939984913832382.8530386     3165746.982    13832380.463
     3164913.387    13832351.146     3164826.962    13832351.146
 3164097.886775113832330.5090168
#Sta/Elev= 30
 4054.15   17.25 4149.21   15.41 4237.26   15.17 4259.33   13.97 4429.37    10.7
 4482.49   10.17 4514.27   11.02 4588.65    8.85 4690.83    7.81 4740.73    5.37
    4896       3  4949.1    4.46 4951.97    -.71 4973.04   -3.53 5040.23    -.22
 5042.76     .22 5052.04    5.19 5229.05    5.62 5250.93    7.58 5290.62     6.5
 5476.02    8.05 5496.81    7.24 5596.07    9.04 5600.71    9.96 5617.83    9.68
 5634.49    8.05 5676.81    9.86 5686.11    9.01 5703.93    9.95 5772.05   10.83
#Mann= 3 ,-1 , 0
 4054.15     .15       0  4949.1     .03       0 5052.04     .15       0
#XS Ineff= 2 , 0
     -68    4940    5.95    5054     -68    5.95
Permanent Ineff=
       F       F
#Block Obstruct= 1 ,-1
 5601.29 5756.08    9.96
Bank Sta=4949.1,5052.04
XS Rating Curve= 0
Exp/Cntr=.5,.3

Type RM Length L Ch R = 1 ,1875.77 ,422.84,400.16,396.39
BEGIN DESCRIPTION:
Railroad
END DESCRIPTION:
XS GIS Cut Line= 5
 3165821.586544913832309.9480559     3165753.649     13832307.04
     3164915.099    13832271.146     3164827.229    13832271.146
 3164097.973486113832266.2797474
#Sta/Elev= 30
  4050.8   15.94 4082.44    14.7 4242.34   14.43 4278.83   16.01 4303.37   13.54
 4382.39   12.73 4428.97   13.95 4573.44   12.99 4609.13   13.87 4659.46   12.82
 4697.55     9.5 4798.97    5.95    4836    6.32  4949.1    4.46 4951.97    -.71
 4973.04   -3.53 5040.23    -.22 5042.76     .22    5051    5.37    5063    6.85
 5089.39    7.35 5100.34    8.15 5196.38    8.51 5209.39   10.67 5277.62   11.74
 5357.57   10.18  5464.4   10.09 5647.47   11.23 5682.53   12.26 5775.26   13.42
#Mann= 3 ,-1 , 0
  4050.8     .15       0  4949.1     .03       0    5051     .15       0
Bank Sta=4949.1,5051
XS Rating Curve= 0
Exp/Cntr=.3,.1

Type RM Length L Ch R = 1 ,1475.611,579.28,711.94,547.91
XS GIS Cut Line= 5
     3165429.577     13831869.25     3164947.637     13831871.71
     3164856.456     13831871.71     3164474.772    13831875.951
     3163997.497    13831874.594
#Sta/Elev= 30
 4472.98   13.45 4503.98   15.05  4559.4   12.38 4634.86   12.85 4736.74    11.1
 4766.74    5.12 4857.42    4.86 4886.74    2.91 4916.74    5.03 4944.35    3.33
 4979.74    3.14 4986.46   -1.33 4997.01   -4.06 5019.32    -.68 5020.26       2
 5061.54    2.55  5117.8    5.64 5143.18    8.57  5167.1    8.16 5246.76   13.53
 5258.12    13.7 5275.04   11.92 5365.82   12.13 5464.42   14.08 5577.86   14.11
 5605.64   16.02 5674.42   15.12 5771.76   17.18 5816.76   14.94  5905.1   16.79
#Mann= 3 ,-1 , 0
 4472.98     .15       0 4979.74     .03       0 5020.26     .15       0
Bank Sta=4979.74,5020.26
XS Rating Curve= 0
Exp/Cntr=.3,.1

Type RM Length L Ch R = 1 ,763.669 ,20.01,20.46,21.71
BEGIN DESCRIPTION:
access road
END DESCRIPTION:
XS GIS Cut Line= 5
     3166000.507    13831349.352     3165257.473    13831308.358
     3165091.943    13831328.627     3164847.319    13831340.866
     3164023.662    13831311.784
#Sta/Elev= 30
 4171.36   12.03 4208.13   10.65 4364.13   10.66  4406.4    8.75 4519.07   10.57
 4547.54   10.39 4571.65   11.86 4590.25   11.02 4628.83   12.41  4736.9    13.1
 4775.34    9.84 4842.73    8.76    4886   11.15  4903.4    8.33 4916.09    8.91
 4940.13    -.83 4974.27   -5.47 5005.67    -.51 5019.95    4.01 5083.91    10.7
 5130.69    11.6 5233.21   11.19 5361.38   12.37 5419.41   14.73 5628.34   15.64
 5698.94   17.07 5748.73   16.11 5981.09   17.11 6074.18   18.76 6151.39   18.79
#Mann= 3 ,-1 , 0
 4171.36     .15       0 4916.09     .03       0 5083.91     .15       0
Bank Sta=4916.09,5083.91
XS Rating Curve= 0
Exp/Cntr=.5,.3

Type RM Length L Ch R = 1 ,743.21  ,55.03,56.3,57.31
BEGIN DESCRIPTION:
access road
END DESCRIPTION:
XS GIS Cut Line= 5
     3166001.609    13831329.382     3165256.803    13831288.291
     3165090.226    13831308.688       3164847.2    13831320.847
     3164023.474    13831287.784
#Sta/Elev= 30
 4170.75   11.55 4201.59   10.27 4368.68   10.14 4406.89    8.36 4571.73    9.28
 4674.42   12.97 4703.36   13.17 4737.39   13.02 4761.99   11.22 4767.44   12.39
 4842.55   10.26 4856.48   10.18 4884.96   12.67 4906.99    11.5 4916.09   10.53
 4940.13    -.83 4974.27   -5.47 5005.67    -.51 5019.95    4.01 5037.25    5.91
 5083.91    10.7 5130.69    11.6 5367.46   12.85 5422.49   15.05 5654.43   16.13
 5699.51   17.36 5756.18   16.27 5960.29   17.07 6074.81   18.87 6152.23   18.66
#Mann= 3 ,-1 , 0
 4170.75     .15       0 4906.99     .03       0 5130.69     .15       0
#XS Ineff= 2 , 0
       0    4905    13.3    5096       0    13.3
Permanent Ineff=
       F       F
Bank Sta=4906.99,5130.69
XS Rating Curve= 0
Exp/Cntr=.5,.3

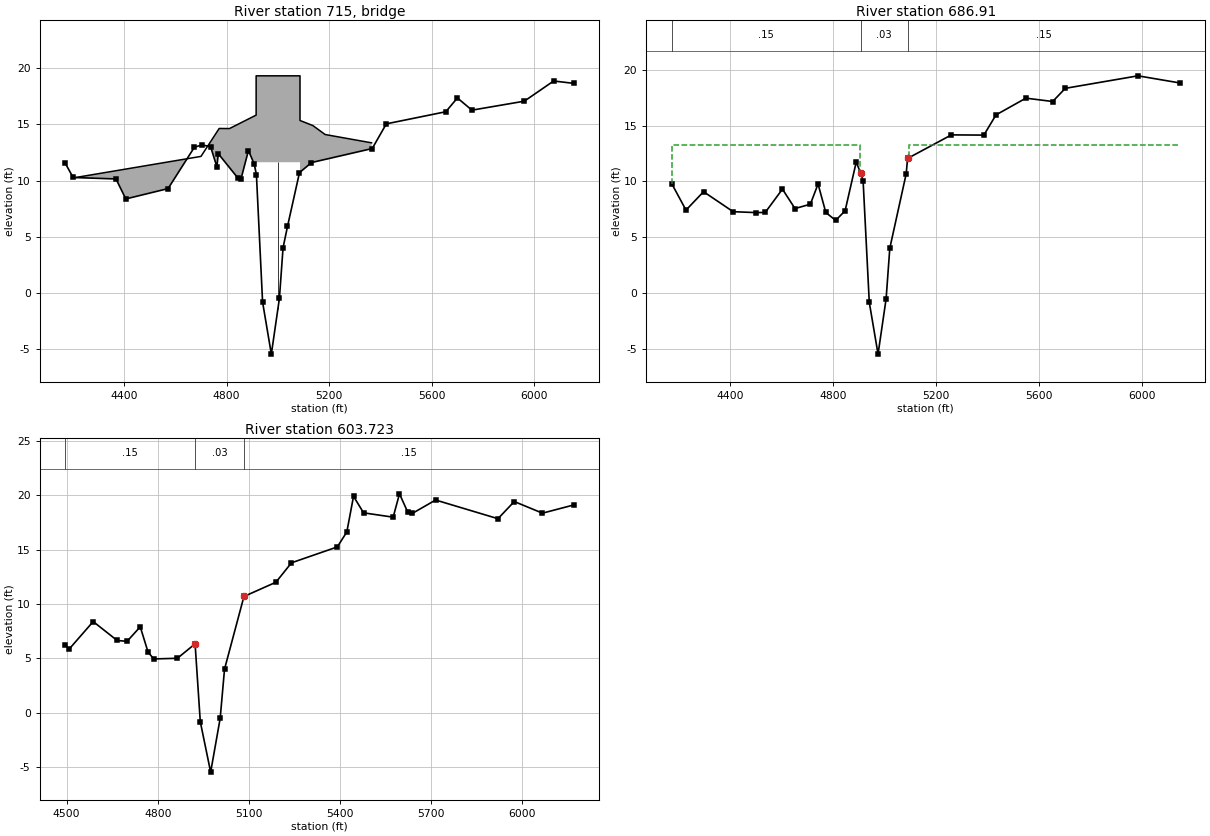
Type RM Length L Ch R = 3 ,715     ,,,
BEGIN DESCRIPTION:
Bridge at access road
END DESCRIPTION:
Bridge Culvert--1,0,-1,-1, 0
Deck Dist Width WeirC Skew NumUp NumDn MinLoCord MaxHiCord MaxSubmerge Is_Ogee
10,25,2.6,0, 14, 15, , , .95, 0, 0,0,,
    4209    4700    4771    4811    4915    4915    4946    5004    5058    5086
    5086    5136    5184    5365
   10.26   12.15   14.64   14.63   15.83   19.33   19.33   19.33   19.33   19.33
   15.35    14.9    14.1   13.36
     -10     -10     -10     -10     -10   11.63   11.63   11.63   11.63   11.63
     -10     -10     -10     -10
    4175    4209    4700    4771    4811    4915    4915    4946    5004    5058
    5086    5086    5136    5184    5365
    9.75   10.26   12.15   14.64   14.63   15.83   19.33   19.33   19.33   19.33
   19.33   15.35    14.9    14.1   13.36
     -10     -10     -10     -10     -10     -10   11.63   11.63   11.63   11.63
   11.63     -10     -10     -10     -10
Pier Skew, UpSta & Num, DnSta & Num=  ,5000, 4 ,5000, 4 , 3 , 3 , 0 ,,
     1.6     1.6     2.5     2.5
     -10    9.13    9.13      12
     1.6     1.6     2.5     2.5
     -10    9.13    9.13      12
BR Coef=-1 , 1 , 0 ,, 0 ,,,.8,-1,2,0,
WSPro=,,,, 1 ,,,, 0 ,,,, 0 ,,,,-1 ,-1 ,-1 , 0 , 0 , 0 , 0 , 0
BC Design=,, 0 ,, 0 ,,,,,,

Type RM Length L Ch R = 1 ,686.91  ,79.45,83.19,84.48
BEGIN DESCRIPTION:
access road
END DESCRIPTION:
XS GIS Cut Line= 5
     3166004.638    13831274.466     3165254.961    13831233.106
     3165085.503    13831253.855     3164846.872    13831265.795
     3164029.814    13831237.063
#Sta/Elev= 30
  4171.2    9.81 4226.94    7.43 4295.24    9.08 4410.38    7.29 4497.76    7.21
 4535.22    7.22 4602.24    9.31 4651.08    7.57 4710.84    7.96 4740.88    9.77
 4770.92    7.22 4809.38    6.51 4846.04    7.37  4889.3   11.73 4906.99   10.73
 4916.09   10.07 4940.13    -.83 4974.27   -5.47 5005.67    -.51 5019.95    4.01
 5083.91    10.7  5089.1   12.06 5259.82   14.17 5386.06   14.15 5433.26   15.96
  5549.6   17.46  5653.8   17.16 5702.94   18.34 5985.68   19.46 6149.24   18.82
#Mann= 3 ,-1 , 0
  4171.2     .15       0 4906.99     .03       0  5089.1     .15       0
#XS Ineff= 2 , 0
       0    4905    13.3    5096       0    13.3
Permanent Ineff=
       F       F
Bank Sta=4906.99,5089.1
XS Rating Curve= 0
Exp/Cntr=.5,.3

Type RM Length L Ch R = 1 ,603.723 ,136.11,603.72,235.25
BEGIN DESCRIPTION:
access road
END DESCRIPTION:
XS GIS Cut Line= 5
     3165688.599    13831177.879     3165252.282    13831152.836
     3165078.634    13831174.099     3164846.394    13831185.718
     3164017.134     13831154.64
#Sta/Elev= 30
 4495.18    6.25 4508.28    5.86 4587.36    8.39 4666.19    6.65 4698.97    6.57
 4742.36    7.91 4767.95    5.59 4786.66    4.95 4864.69    5.01    4923    6.34
 4940.13    -.83 4974.27   -5.47 5005.67    -.51 5019.95    4.01 5083.91    10.7
 5189.17   12.01 5240.51    13.8 5391.38   15.26 5422.77   16.64 5444.87   19.92
 5477.97    18.4 5575.42      18 5596.23   20.15 5622.87    18.5  5638.1   18.34
 5715.17   19.58 5920.66   17.86 5974.29   19.44 6067.21   18.37 6169.53   19.12
#Mann= 3 ,-1 , 0
 4495.18     .15       0    4923     .03       0 5083.91     .15       0
Bank Sta=4923,5083.91
XS Rating Curve= 0
Exp/Cntr=.3,.1

Chan Stop Cuts=-1

--- G112_00_00.g02 (geometry) ---

Geom Title=G112-00-00 June 2007 (Floodway)
Version=Version 3.0.1  Mar 2001

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
River Reach=G112-00-00   ,G112-00-00_0006